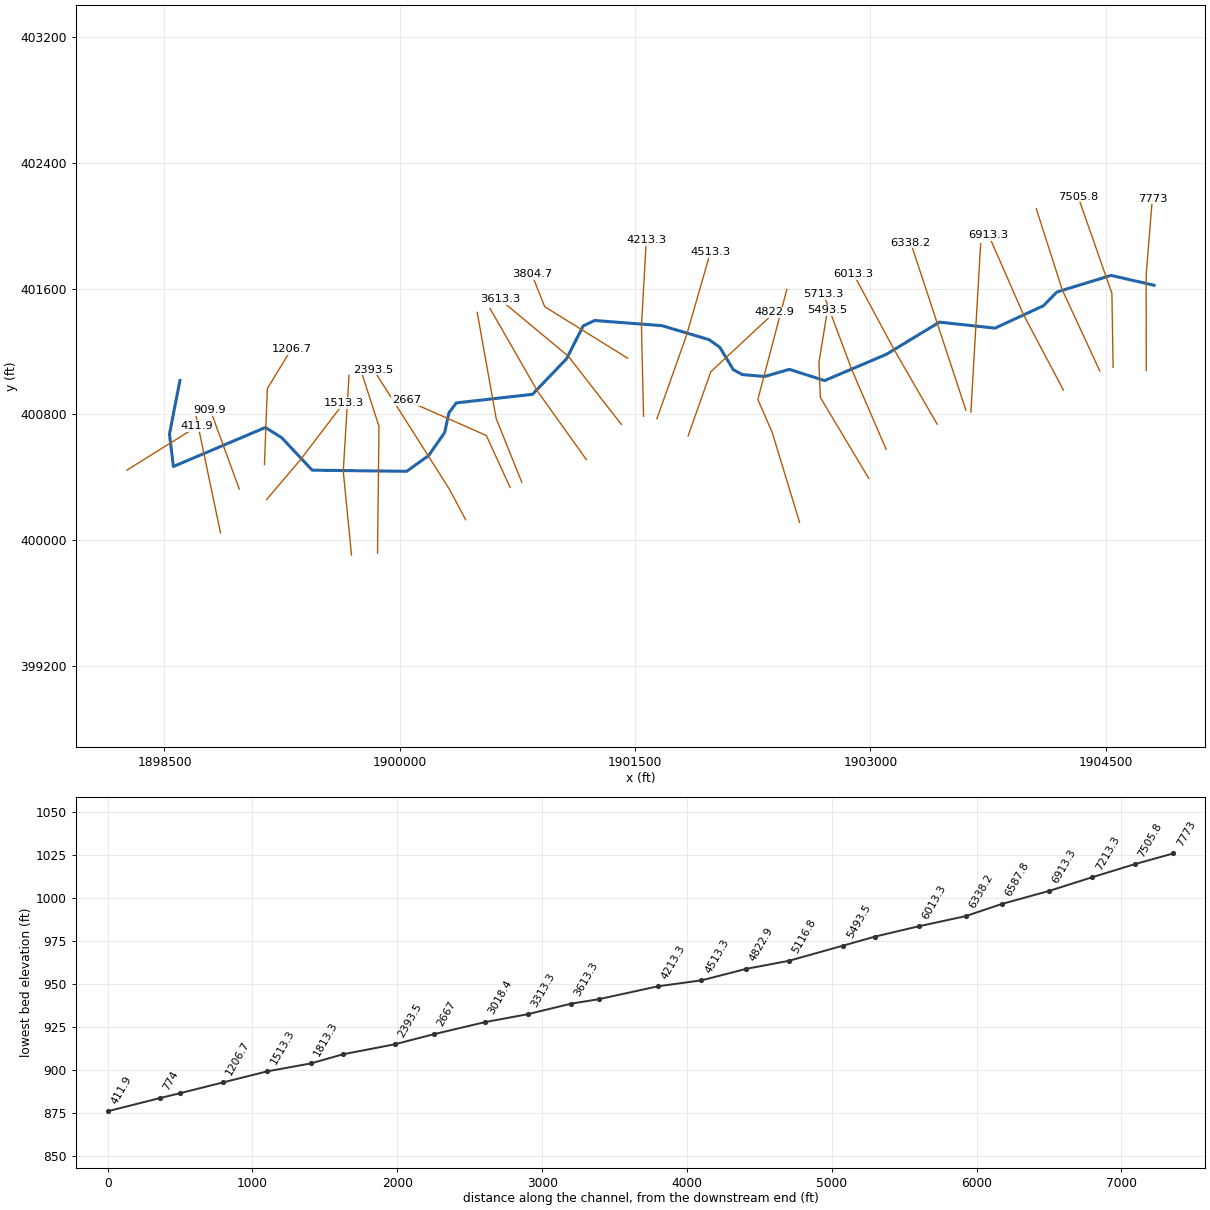
--- DmpsyBrch.prj (project) ---

Proj Title=DmpsyBrch
Current Plan=p01
Default Exp/Contr=0,0
English Units
Geom File=g01
Flow File=f01
Plan File=p01
BEGIN DESCRIPTION:
END DESCRIPTION:
DSS Export Rating Curves= 0
DSS Export Rating Curve Sorted= 0
DSS Export Volume Flow Curves= 0
DXF OffsetX= 0
DXF OffsetY= 0
DXF ScaleX= 0
DXF ScaleY= 0

--- DmpsyBrch.p01 (plan) ---

Plan Title=Floodplain
Program Version=4.00
Geom File=g01
Flow File=f01
K Sum by GR=0
Std Step Tol=0.01
Critical Tol=0.01
Num of Std Step Trials=20
Max Error Tol=0.3
Flow Tol Ratio=0.001
Split Flow NTrial=30
Split Flow Tol=0.02
Split Flow Ratio=0.02
Log Output Level=0
Friction Slope Method=1
Unsteady Friction Slope Method=2
Unsteady Bridges Friction Slope Method=1
Global Log Level=0
CheckData=False
Run HTab=0
Run UNet=0
Run PostProcess=0
UNET Theta=0
UNET Theta Warmup=0
UNET ZTol=0
UNET ZSATol=0
UNET MxIter=0
UNET MaxInSteps=0
UNET DtIC=0
UNET DtMin=0
UNET MaxCRTS=0
UNET WFStab=0
UNET SFStab=0
UNET WFX=0
UNET SFX=0
UNET DSS MLevel=0
UNET DZMax Abort=0
UNET Convert EG Bridges=0
UNET Use Existing IB Tables=0
UNET Froude Limit=0
UNET Froude Power=0
Write IC File=0
Echo Input=False
Echo Output=False
Write Detailed=0

--- DmpsyBrch.f01 (steady flow) ---

Flow Title=NFF Regression Equation
Program Version=4.00
Number of Profiles=1
Profile Names=P100yr
River Rch & RM=DmpsyBrch,Main      ,7773
764.5961
River Rch & RM=DmpsyBrch,Main      ,7505.8
764.5961
River Rch & RM=DmpsyBrch,Main      ,7213.3
1130.957
River Rch & RM=DmpsyBrch,Main      ,5116.8
1237.828
River Rch & RM=DmpsyBrch,Main      ,4822.9
2049.573
Boundary for River Rch & Prof#=DmpsyBrch,Main      ,1
Up Type=0
Dn Type=3
Dn Slope=0.020868

--- DmpsyBrch.g01 (geometry) ---

Geom Title=USGS 3m DEM
Program Version=4.10

River Reach=DmpsyBrch       ,Main
Reach XY= 30
     1904807.694      401621.251      1904533.48      401683.751
     1904188.393       401578.34     1904102.833      401491.043
     1903793.805      401348.682     1903439.638      401386.876
     1903101.097      401182.015     1902707.577      401015.312
     1902483.041      401086.529     1902325.055       401041.39
     1902182.694      401053.543     1902125.402      401084.793
     1902039.734      401226.615     1901970.888      401275.765
     1901670.541      401364.307     1901241.721      401397.293
     1901168.805       401362.57     1901062.902      401154.237
      1900845.67      400928.008     1900360.222      400873.558
     1900312.915      400810.125     1900285.561      400684.525
     1900182.694      400537.918     1900043.535      400438.614
     1899441.374      400445.904      1899246.93      400652.501
     1899142.998      400717.207      1898556.85      400469.339
     1898531.652       400675.07     1898598.392      401015.928

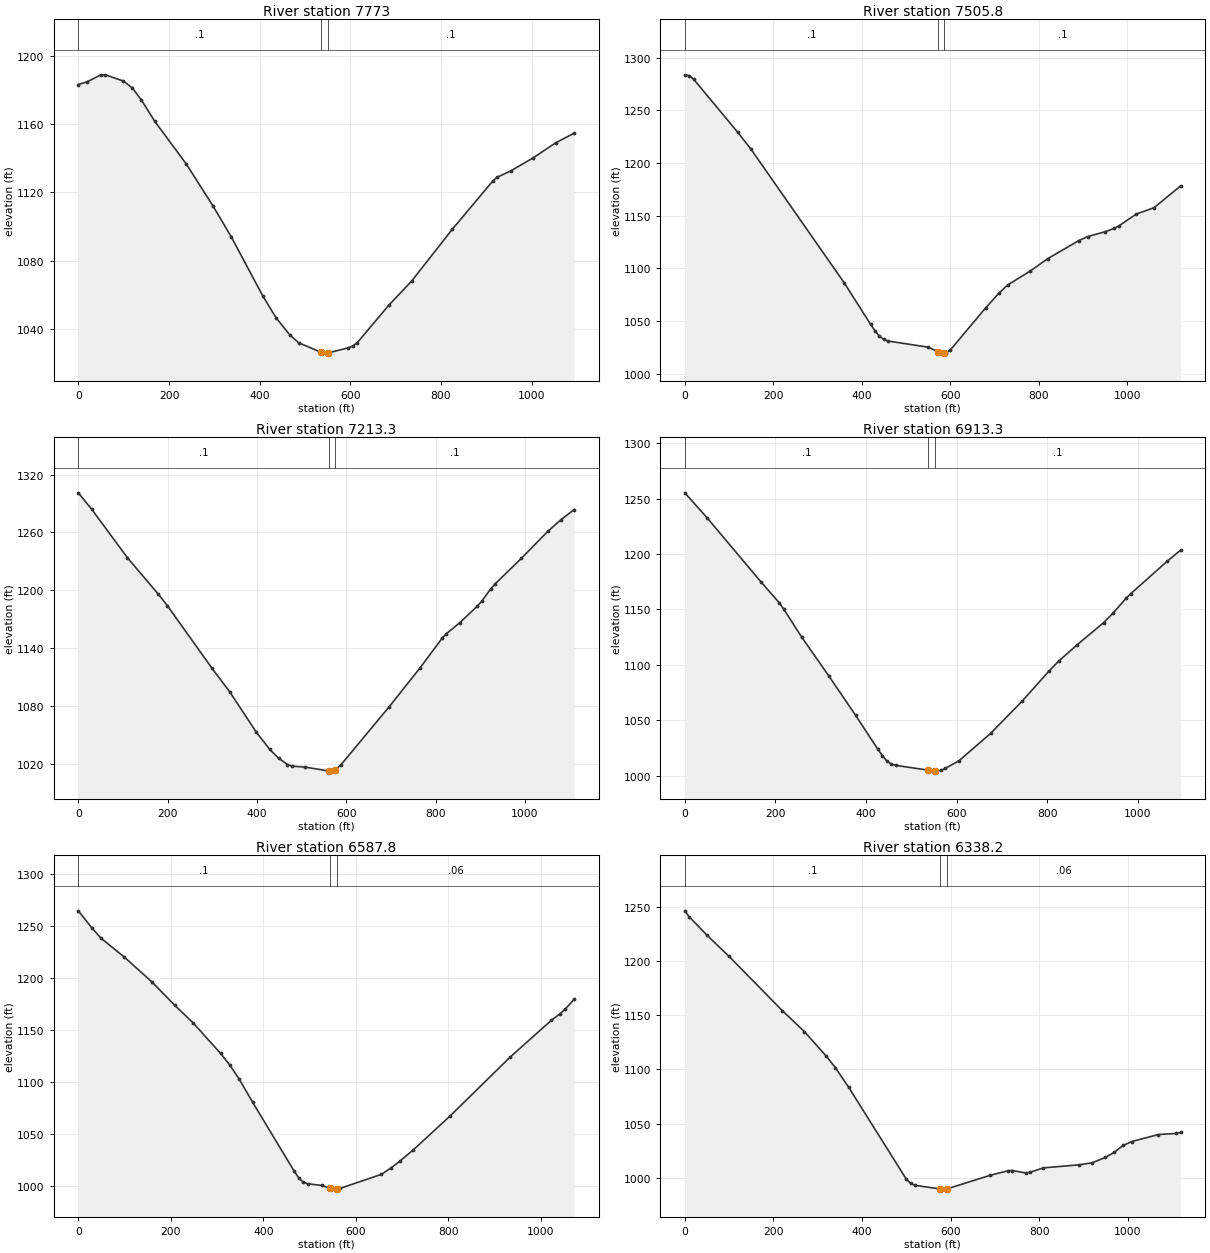
Type RM Length L Ch R = 1 ,7773    ,259.4,267.1,274.9
XS GIS Cut Line= 3
      1904757.89       401078.86     1904757.299       401684.18
     1904796.541       402170.86
#Sta/Elev= 30
       0 1183.08    19.8 1184.71    49.6 1188.75    59.5 1188.76    99.2 1185.13
   119.1 1181.07   138.9 1174.11   168.7 1161.52   238.2 1136.56   297.7 1111.75
   337.4 1093.93   406.8 1059.46   436.6 1046.48   466.4  1036.6   486.2    1032
   535.1 1026.49   545.8 1025.96   550.1 1026.04   595.4 1029.05   605.3 1030.08
   615.3 1032.12     685 1054.06   734.9 1068.05   824.5 1098.31   914.2 1126.68
   924.2 1128.92   954.1  1132.6  1003.9 1140.31  1053.7 1149.14  1093.6  1154.6
#Mann= 3 , 0 , 0
       0      .1       0   535.1    .045       0   550.1      .1       0
Bank Sta=535.1,550.1
XS Rating Curve= 0 ,0
Exp/Cntr=0.3,0.1

Type RM Length L Ch R = 1 ,7505.8  ,290,292.2,291.7
XS GIS Cut Line= 3
     1904546.567      401099.648     1904538.951      401569.745
     1904323.476      402183.953
#Sta/Elev= 30
       0 1283.58      10 1282.77      20 1279.41     120 1228.93     150 1212.86
   360.1 1086.58   420.1 1047.04   430.2 1040.77   440.2  1035.7   450.2 1032.64
   460.2 1031.12   550.3 1025.37   571.9 1021.25   580.3 1019.72   586.9 1019.71
   590.3 1019.71   600.3 1022.63   680.4 1062.71   710.5 1076.65   730.5 1084.48
   780.6  1097.4   820.6 1109.29   890.8 1126.41   910.8 1130.18   950.8 1134.86
   970.9 1138.02   980.9 1140.19  1020.9 1151.58    1061  1157.6  1121.1 1178.29
#Mann= 3 , 0 , 0
       0      .1       0   571.9    .045       0   586.9      .1       0
Bank Sta=571.9,586.9
XS Rating Curve= 0 ,0
Exp/Cntr=0.3,0.1

Type RM Length L Ch R = 1 ,7213.3  ,298.9,300.1,302.3
XS GIS Cut Line= 3
     1904461.816      401076.238     1904222.805      401591.423
      1904056.91      402107.547
#Sta/Elev= 30
       0 1301.19    29.9  1284.1   109.6 1233.97   179.4 1195.78   199.3 1184.02
   298.9 1119.21   338.8 1094.65   398.6  1052.5   428.4 1034.78   448.4 1025.59
   468.3 1019.03   478.3 1017.35   508.2 1016.33   560.4 1012.33   567.9 1012.16
   575.4 1013.58   587.6 1018.55   696.1  1079.1   765.1  1119.4   814.4 1150.11
   824.2 1155.02   853.8 1166.23   893.2 1183.47   903.1 1188.52   922.8 1201.15
   932.6 1206.39   991.8 1233.12  1050.9  1261.1  1080.5 1273.24  1110.1 1283.74
#Mann= 3 , 0 , 0
       0      .1       0   560.4    .045       0   575.4      .1       0
Bank Sta=560.4,575.4
XS Rating Curve= 0 ,0
Exp/Cntr=0.3,0.1

Type RM Length L Ch R = 1 ,6913.3  ,337.9,325.5,314.8
XS GIS Cut Line= 3
     1904229.751      400955.099     1903974.133      401436.951
     1903753.338      401939.874
#Sta/Elev= 30
       0 1255.24    49.6 1232.54   168.6 1174.66   208.3 1156.13   218.2 1150.47
   257.8  1125.2   317.4 1090.35   376.9  1054.6   426.4 1023.79   436.4 1018.03
   446.3 1013.17   456.2  1010.4   466.1 1009.33     538 1004.95     553 1004.19
   555.4 1004.13   565.4 1004.83   575.4  1006.7   605.4  1013.5   675.3 1038.22
   745.2 1067.45   805.1 1094.88   825.1 1103.25     865 1117.69   924.9  1138.2
   944.9 1146.43   974.9 1160.38   984.9 1164.37  1064.8 1193.42  1094.7 1203.55
#Mann= 3 , 0 , 0
       0      .1       0     538    .045       0     553      .1       0
Bank Sta=538,553
XS Rating Curve= 0 ,0
Exp/Cntr=0.3,0.1

Type RM Length L Ch R = 1 ,6587.8  ,241,249.6,258.1
XS GIS Cut Line= 2
     1903640.091      400814.822     1903702.388      401885.182
#Sta/Elev= 30
       0 1264.19    29.8 1247.46    49.6 1237.64    99.3 1219.78   158.8 1195.97
   208.5 1173.39   248.2 1156.44   307.8 1127.02   327.6 1115.89   347.5  1102.6
   377.2 1079.94   466.6 1013.98   476.5 1007.39   486.4 1003.29   496.4  1001.7
   526.2 1000.16   543.3   997.6   555.9  996.59   558.3  996.76   565.9  997.29
   655.2 1010.77   675.1 1016.61   694.9 1023.37   724.7  1034.5   804.1 1067.01
   933.2 1123.29  1022.5 1158.78  1042.4 1165.46  1052.3 1169.51  1072.2 1179.07
#Mann= 3 , 0 , 0
       0      .1       0   543.3    .045       0   558.3     .06       0
Bank Sta=543.3,558.3
XS Rating Curve= 0 ,0
Exp/Cntr=0.3,0.1

Type RM Length L Ch R = 1 ,6338.2  ,320.2,324.8,328.7
XS GIS Cut Line= 2
     1903608.196      400827.806     1903256.626      401890.655
#Sta/Elev= 30
       0 1246.04      10  1240.5      50  1223.6     100 1204.03   219.9 1154.14
   269.9 1134.78   319.8 1111.93   339.8 1101.58   369.8 1083.52   499.8  998.95
   509.8  994.78   519.8     993   575.9  989.75   579.7  989.51   590.9  989.63
   689.7 1002.26   729.7 1006.44   739.7 1006.68   769.6 1004.39   779.6 1005.07
   809.6  1009.1   889.6 1011.89   919.6 1013.76   949.6 1018.69   969.6 1023.45
   989.6 1029.76  1009.5 1033.41  1069.5 1039.86  1109.5 1040.83  1119.5 1041.72
#Mann= 3 , 0 , 0
       0      .1       0   575.9    .045       0   590.9     .06       0
Bank Sta=575.9,590.9
XS Rating Curve= 0 ,0
Exp/Cntr=0.3,0.1

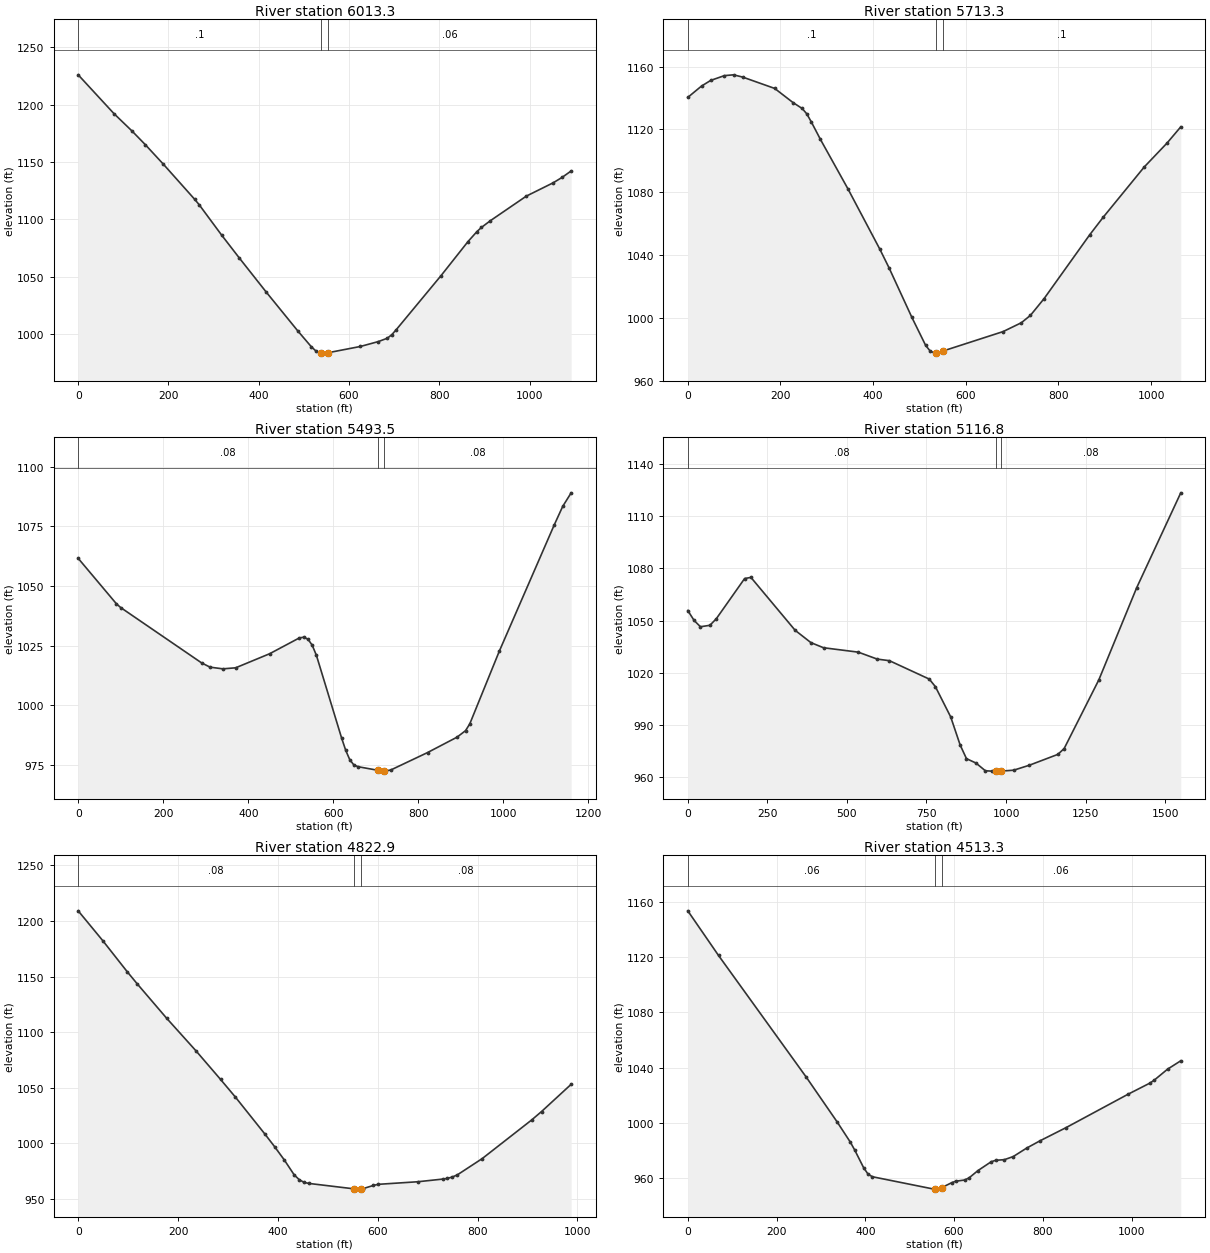
Type RM Length L Ch R = 1 ,6013.3  ,302.6,299.9,296.9
XS GIS Cut Line= 3
     1903424.783      400738.582     1903151.247       401211.05
     1902892.059      401692.015
#Sta/Elev= 30
       0 1226.03    79.4 1192.18   119.1 1177.16   148.9 1165.11   188.6 1148.23
   258.1 1117.58     268 1112.91   317.6 1086.53   357.3 1066.32   416.9 1036.65
   486.4 1003.03   516.2   989.3   526.1  985.68   538.4  983.81   545.9  983.59
   553.4  983.92   625.4   989.4   665.1  993.66     685  996.58   694.9  999.67
   704.9 1004.09   804.2 1051.21   863.8 1080.82   883.7 1089.54   893.6 1093.12
   913.5 1099.01     993 1120.38  1052.6    1132  1072.4 1136.73  1092.3  1142.3
#Mann= 3 , 0 , 0
       0      .1       0   538.4    .045       0   553.4     .06       0
Bank Sta=538.4,553.4
XS Rating Curve= 0 ,0
Exp/Cntr=0.3,0.1

Type RM Length L Ch R = 1 ,5713.3  ,228,219.7,213.2
XS GIS Cut Line= 3
      1903099.81      400578.858     1902883.893       401077.13
     1902700.748      401564.894
#Sta/Elev= 30
       0 1140.42    29.6 1147.62    49.4 1151.22      79 1154.27    98.7 1154.78
   118.5 1153.34   187.6 1146.12   227.1 1137.13   246.8 1133.38   256.7    1130
   266.6 1124.83   286.3 1113.68   345.6 1082.25   414.7 1043.72   434.4 1031.95
   483.8 1000.34   513.4  982.59   523.3  978.93   533.2  977.65   535.5  977.75
   550.5  978.96   680.7  991.37     720  996.99   739.6 1001.68   769.1 1012.35
   867.4 1052.91   896.9 1064.22   985.4 1096.17  1034.6 1111.39  1064.1 1121.67
#Mann= 3 , 0 , 0
       0      .1       0   535.5    .045       0   550.5      .1       0
Bank Sta=535.5,550.5
XS Rating Curve= 0 ,0
Exp/Cntr=0.3,0.1

Type RM Length L Ch R = 1 ,5493.5  ,383.8,376.7,367.5
XS GIS Cut Line= 4
     1902989.303      400393.246     1902680.525      400908.206
     1902671.352      401129.131     1902725.904      401462.626
#Sta/Elev= 30
       0  1061.6    90.1 1042.51   100.1 1040.96   290.2 1017.79   310.2 1015.99
   340.2 1015.29   370.3 1015.72   450.3 1021.62   520.4 1028.27   530.4 1028.54
   540.4 1027.72   550.4 1025.21   560.4  1020.9   619.7  986.22   629.3  981.11
   638.9  977.16   648.5     975   658.1  974.28   705.1  972.76   715.8  972.42
   720.1  972.42     735  972.88   821.6  980.19   891.1  986.66     911  989.37
     921  992.21   990.5  1022.7  1119.7 1075.62  1139.6 1083.37  1159.5 1089.06
#Mann= 3 , 0 , 0
       0     .08       0   705.1    .045       0   720.1     .08       0
Bank Sta=705.1,720.1
XS Rating Curve= 0 ,0
Exp/Cntr=0.3,0.1

Type RM Length L Ch R = 1 ,5116.8  ,306.3,293.8,282.9
XS GIS Cut Line= 4
     1902547.912      400114.684     1902374.212      400683.938
     1902282.138       400895.71     1902466.944       401594.49
#Sta/Elev= 30
       0 1055.76    19.8 1050.08    39.7 1046.44    69.4 1047.27    89.3 1050.97
   178.6 1074.13   198.4 1074.77   337.3  1044.4   386.9 1037.32   426.5 1034.39
   535.6 1031.86   595.2 1027.87   633.6 1026.95   758.7 1016.39     778 1012.03
   826.1  994.65   855.8  978.53   875.6  970.71   905.3  968.21     935  963.75
   954.8  963.55     969  963.55     984  963.55  1024.1  964.09  1073.6  966.97
  1162.7  973.16  1182.5  976.51  1291.5 1015.96  1410.3 1068.81  1548.9 1123.33
#Mann= 3 , 0 , 0
       0     .08       0     969    .045       0     984     .08       0
Bank Sta=969,984
XS Rating Curve= 0 ,0
Exp/Cntr=0.3,0.1

Type RM Length L Ch R = 1 ,4822.9  ,298.6,309.4,321.5
XS GIS Cut Line= 3
     1901837.549      400663.623     1901982.238      401071.382
     1902388.681      401448.888
#Sta/Elev= 30
       0 1209.17    49.2 1182.36    98.3 1154.35     118 1143.62     177 1112.66
     236 1083.22   285.2 1057.52   314.7 1041.76   373.7 1008.57   393.3  997.12
     413  985.01   432.7  971.66   442.6  967.45   452.5  964.92   462.4  963.99
   551.9  959.16   561.4  958.88   566.9  959.19   571.4  959.44   591.2  962.19
   601.1   963.2   680.3  965.52   729.8  967.89   739.7  968.55   749.6  969.82
   759.6  971.76   809.1   986.3   908.1 1021.02     928 1028.63   987.4 1053.16
#Mann= 3 , 0 , 0
       0     .08       0   551.9    .045       0   566.9     .08       0
Bank Sta=551.9,566.9
XS Rating Curve= 0 ,0
Exp/Cntr=0.3,0.1

Type RM Length L Ch R = 1 ,4513.3  ,291.8,300,305.1
XS GIS Cut Line= 3
     1901638.792      400772.817     1901828.105      401304.741
     1901979.387      401829.668
#Sta/Elev= 30
       0 1153.35    69.3 1121.07   267.4 1032.94   336.8 1000.65   366.5  986.05
   376.4   980.3   396.2   967.7   406.1  963.06     416  961.14   554.7  952.19
   557.1  952.25   564.6  952.43   572.1  953.25   594.4   956.8   604.3  957.94
   624.2  958.79   634.1  960.39     654  965.63   683.8     972   693.7  973.01
   713.6   973.5   733.5  975.75   763.3  981.79   793.1  987.02   852.6  996.68
   991.7 1020.71  1041.4 1028.84  1051.3 1031.01  1081.1 1038.89  1110.9 1044.96
#Mann= 3 , 0 , 0
       0     .06       0   557.1    .045       0   572.1     .06       0
Bank Sta=557.1,572.1
XS Rating Curve= 0 ,0
Exp/Cntr=0.3,0.1

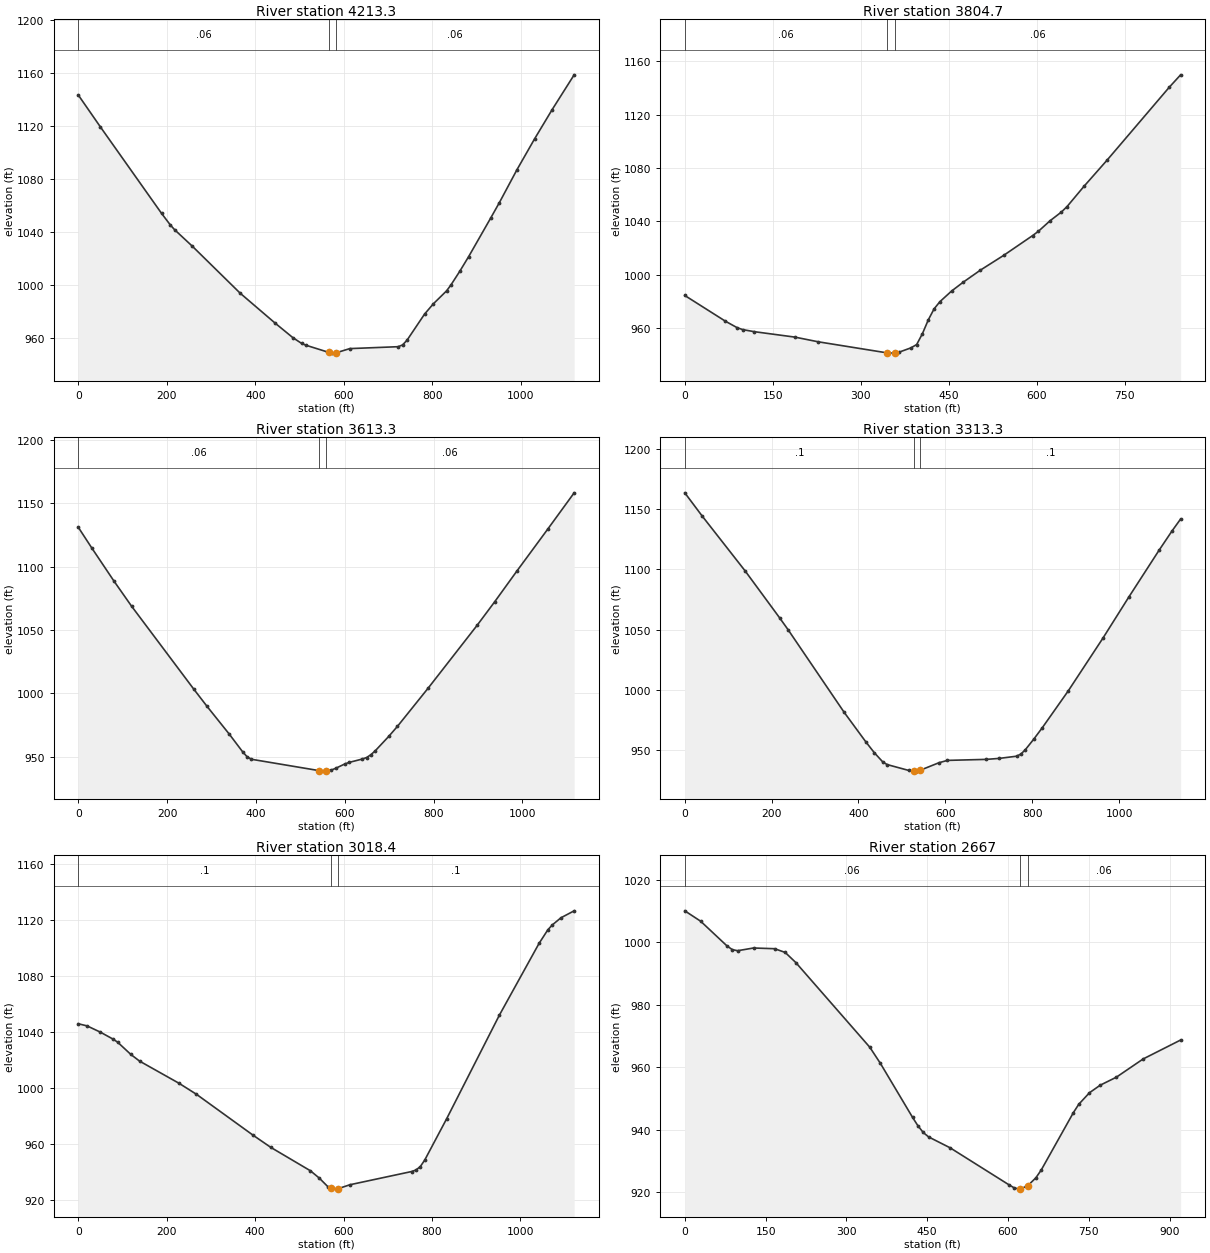
Type RM Length L Ch R = 1 ,4213.3  ,386.1,408.6,432.9
XS GIS Cut Line= 3
      1901553.46      400788.631     1901540.284       401362.35
     1901571.151      401908.295
#Sta/Elev= 30
       0 1143.33    49.5 1119.51     188 1054.18   207.8 1045.45   217.7 1041.78
   257.2 1029.52   366.1  993.85   445.2  971.27   484.8  960.44   504.6   956.1
   514.5   954.7   566.4  949.28   573.9  948.75   581.4  948.87   613.6  952.16
     723   953.6   732.9  954.95   742.9  958.47   782.6  978.19   802.5  985.96
   832.4  995.73   842.3 1000.22   862.2 1010.49   882.1 1021.46   931.8 1050.46
   951.7 1062.27   991.4 1087.05  1031.2 1110.29    1071  1132.4  1120.7 1158.61
#Mann= 3 , 0 , 0
       0     .06       0   566.4    .045       0   581.4     .06       0
Bank Sta=566.4,581.4
XS Rating Curve= 0 ,0
Exp/Cntr=0.3,0.1

Type RM Length L Ch R = 1 ,3804.7  ,199.6,191.3,188.1
XS GIS Cut Line= 3
     1901452.809      401157.318     1900923.161      401485.279
     1900840.732      401692.228
#Sta/Elev= 30
       0  984.43    69.2  965.18      89  960.38    98.9  958.85   118.7  957.31
   187.9  953.24   227.4  949.75   344.2   941.5     356  941.25   359.2  941.51
   365.9  942.04   385.6  945.18   395.5  947.68   405.4  955.91   415.3  966.15
   425.2   974.4   435.1  979.79   454.9   987.7   474.6   994.3   504.3 1003.45
   543.9 1014.48   593.3 1029.31   603.2 1032.55     623  1040.4   642.3 1046.92
     652 1051.04   681.1 1066.31   719.8 1085.58   826.4 1140.46   845.7 1149.72
#Mann= 3 , 0 , 0
       0     .06       0   344.2    .045       0   359.2     .06       0
Bank Sta=344.2,359.2
XS Rating Curve= 0 ,0
Exp/Cntr=0.3,0.1

Type RM Length L Ch R = 1 ,3613.3  ,300.6,299.8,291.7
XS GIS Cut Line= 3
     1901411.722       400737.18     1901073.442      401170.525
     1900637.142      401532.634
#Sta/Elev= 30
       0 1130.95      30 1114.84      80 1088.71   119.9 1068.77   259.9 1003.38
   289.9  989.74   339.8  967.91   369.8  954.02   379.8  950.08   389.8  948.02
   542.2  939.06   549.8  938.66   557.2  938.67   559.7  938.68   569.6  939.49
   579.6  940.89   599.5   944.2   609.4   945.5   639.3  948.17   649.2  949.38
   659.2  951.68   669.1  954.84     699  966.02   718.8  974.01   788.5  1004.4
   897.9 1053.56   937.7 1072.24   987.4 1096.34  1057.1 1129.51  1116.7 1158.19
#Mann= 3 , 0 , 0
       0     .06       0   542.2    .045       0   557.2     .06       0
Bank Sta=542.2,557.2
XS Rating Curve= 0 ,0
Exp/Cntr=0.3,0.1

Type RM Length L Ch R = 1 ,3313.3  ,304.9,294.8,287
XS GIS Cut Line= 3
     1901189.452      400512.646     1900877.688      400947.711
     1900575.067      401473.412
#Sta/Elev= 30
       0 1163.68    39.6  1144.6   138.8 1098.89   218.1 1059.97   237.9 1049.96
   366.7  981.51   416.3  957.12   436.1  947.95   455.9  940.16   465.8  937.98
   515.4  933.12   525.3  932.52   527.7  932.54   535.2  932.61   542.7  933.34
     585  939.46   604.8  941.44   694.3  942.28   724.2   943.1     764  944.91
   773.9  946.72   783.8  950.13   803.7  959.12   823.6  968.75   883.3  999.32
   962.8 1042.94  1022.5 1077.12  1092.1 1115.96  1121.9 1131.96  1141.8 1141.94
#Mann= 3 , 0 , 0
       0      .1       0   527.7    .045       0   542.7      .1       0
Bank Sta=527.7,542.7
XS Rating Curve= 0 ,0
Exp/Cntr=0.3,0.1

Type RM Length L Ch R = 1 ,3018.4  ,329.3,351.4,373.5
XS GIS Cut Line= 3
     1900777.434      400369.232     1900614.492      400773.236
     1900493.241      401448.759
#Sta/Elev= 30
       0 1045.91    19.8  1044.4    49.5 1039.99    79.2 1034.86    89.1 1032.73
   118.8 1024.03   138.6 1019.27   227.7 1003.48   267.3   995.6     396  966.27
   435.6   957.7   525.1  941.03     545  935.86   564.9  929.59   571.7  928.47
   574.9  927.94   584.8  927.93   586.7  928.13   614.7  931.07   753.9  940.47
   763.9  941.57   773.8  944.01   783.8  948.68   833.5   978.2   952.8 1052.13
  1042.4 1103.22  1062.3 1112.93  1072.2 1116.38  1092.1 1121.56  1121.9  1126.5
#Mann= 3 , 0 , 0
       0      .1       0   571.7    .045       0   586.7      .1       0
Bank Sta=571.7,586.7
XS Rating Curve= 0 ,0
Exp/Cntr=0.3,0.1

Type RM Length L Ch R = 1 ,2667    ,286.6,273.3,259.7
XS GIS Cut Line= 3
     1900702.939      400336.315     1900551.355      400666.254
     1900040.999      400890.741
#Sta/Elev= 30
       0 1009.98    29.4 1006.66    78.5  998.73    88.3  997.56    98.1  997.22
   127.6  998.09   166.8  997.86   186.4  996.67   206.1  993.44   343.5  966.34
   363.1   961.2   422.8  943.93   432.8  941.23   442.7  939.07   452.7  937.65
   492.5  934.18     602  922.32     612  921.31   621.5  920.97     622  920.95
   636.5     922   651.8  924.56   661.8  927.07   721.5  945.43   731.5   948.1
   751.4  951.79   771.3   954.2   801.2  956.75     851  962.59   920.6  968.65
#Mann= 3 , 0 , 0
       0     .06       0   621.5    .045       0   636.5     .06       0
Bank Sta=621.5,636.5
XS Rating Curve= 0 ,0
Exp/Cntr=0.3,0.1

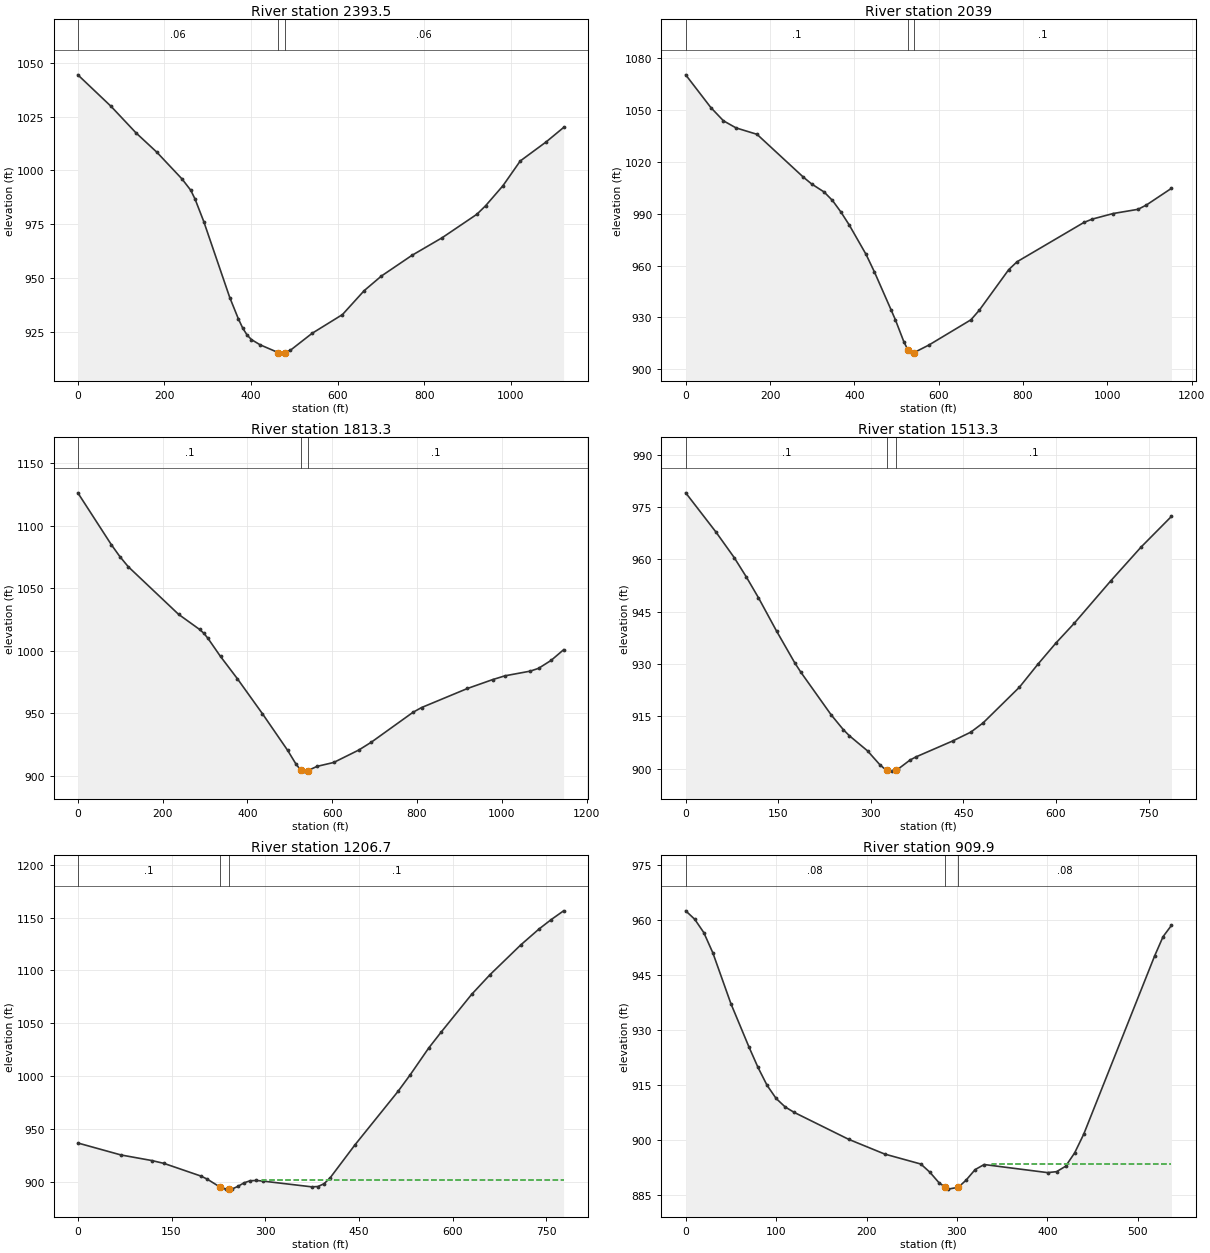
Type RM Length L Ch R = 1 ,2393.5  ,367.3,354.3,341.6
XS GIS Cut Line= 3
     1900419.601      400130.906     1900315.688      400325.578
     1899831.944      401085.691
#Sta/Elev= 30
       0 1044.45    76.8 1029.77   134.3 1017.46   182.3 1008.49   240.7  995.99
   260.7  990.78   270.7  986.66   290.8  976.21   350.8  940.88   370.8   930.9
   380.8  926.64   390.9   923.4   400.9  921.31   420.9  918.88   463.3  915.21
   470.9  915.01   478.3   915.2     491  916.37     541  924.23   611.1  932.95
   661.2  944.07   701.2   950.9   771.3  960.46   841.4   968.7   921.4  979.59
   941.5  983.54   981.5  992.84  1021.6 1004.38  1081.6 1013.28  1121.7 1019.97
#Mann= 3 , 0 , 0
       0     .06       0   463.3    .045       0   478.3     .06       0
Bank Sta=463.3,478.3
XS Rating Curve= 0 ,0
Exp/Cntr=0.3,0.1

Type RM Length L Ch R = 1 ,2039    ,223.3,225.6,224.4
XS GIS Cut Line= 3
     1899857.964      399918.498     1899867.154      400724.129
     1899760.622      401053.656
#Sta/Elev= 30
       0 1070.43    59.7 1051.45    89.5 1043.81   119.4 1039.69   169.1 1035.98
   278.5 1011.29   298.4 1007.27   328.2 1002.58   348.1  997.66     368     991
   387.9  983.44   427.7  966.44   447.6  956.25   487.4  934.12   497.3  928.54
   517.2  915.92   526.5  911.32   537.1  909.26   541.5  909.57   576.9  913.97
   676.4  928.56   696.3  934.13   765.9  957.57   785.8  962.18   944.2  984.92
     964  986.87  1013.5   990.1  1072.8  992.55  1092.6  995.05    1152 1004.71
#Mann= 3 , 0 , 0
       0      .1       0   526.5    .045       0   541.5      .1       0
Bank Sta=526.5,541.5
XS Rating Curve= 0 ,0
Exp/Cntr=0.3,0.1

Type RM Length L Ch R = 1 ,1813.3  ,318.3,300.2,286.7
XS GIS Cut Line= 3
     1899692.065      399906.799     1899639.521      400438.689
      1899676.29      401048.674
#Sta/Elev= 30
       0 1126.35    79.2 1084.81      99 1075.45   118.8 1067.34   237.6 1029.23
     287 1017.18   296.9 1014.18   306.8 1010.07   336.5  995.53   376.1  977.84
   435.5  949.72   494.9  920.45   514.7   909.4   524.6  905.23     527  904.91
   534.5  903.89     542  904.23     564  907.68   603.5  910.82   662.6  920.76
   692.2  927.03   790.7  950.98   810.5  954.69   918.9  969.96     978  977.02
  1007.6   980.1  1066.7  983.81  1086.4  986.04    1116  992.38  1145.6 1000.93
#Mann= 3 , 0 , 0
       0      .1       0     527    .045       0     542      .1       0
Bank Sta=527,542
XS Rating Curve= 0 ,0
Exp/Cntr=0.3,0.1

Type RM Length L Ch R = 1 ,1513.3  ,291.4,306.6,320.6
XS GIS Cut Line= 3
     1899150.288      400258.495     1899366.933      400512.622
     1899642.229      400872.764
#Sta/Elev= 30
       0   979.1    49.1  967.84    78.6  960.53    98.2  954.99   117.9  949.02
   147.3  939.44   176.8  930.33   186.6  927.66   235.7  915.44   255.4   911.2
   265.2  909.45   294.6  905.12   314.3   901.2   324.1  899.69   326.4   899.6
   333.9   899.3   341.4  899.71   343.8  899.84   363.5  902.48   373.4   903.4
   432.5  907.94     462  910.48   481.8  913.11   540.9  923.39   570.4  929.89
     600  936.04   629.6  941.69   688.7  953.84     738  963.56   787.2  972.35
#Mann= 3 , 0 , 0
       0      .1       0   326.4    .045       0   341.4      .1       0
Bank Sta=326.4,341.4
XS Rating Curve= 0 ,0
Exp/Cntr=0.3,0.1

Type RM Length L Ch R = 1 ,1206.7  ,287.9,296.8,305.7
XS GIS Cut Line= 3
     1899137.134      400482.105     1899155.549      400964.839
     1899309.437      401216.055
#Sta/Elev= 30
       0  936.55      69  925.22   118.3  919.94     138   917.2   197.2  905.19
     207  902.35   227.4  894.89   236.6  892.84   242.4  892.86   246.5  892.87
   256.3  895.45   266.2  898.84     276  900.79   285.9  901.04   295.8  900.49
   374.6     895   384.5  895.32   394.4  898.04   404.2  903.75   443.6  934.73
   512.6  985.44   532.2 1001.23   561.6 1026.43   581.3 1041.36   630.4 1077.32
   659.8 1095.98     709 1124.16   738.4 1139.33     758 1148.29   777.7 1156.52
#Mann= 3 , 0 , 0
       0      .1       0   227.4    .045       0   242.4      .1       0
#XS Ineff= 2 , 0
                          295.56          901.31
Permanent Ineff=
       F       F
Bank Sta=227.4,242.4
XS Rating Curve= 0 ,0
Exp/Cntr=0.3,0.1

Type RM Length L Ch R = 1 ,909.9   ,139,135.6,132.2
XS GIS Cut Line= 3
     1898976.661      400325.578      1898804.35      400795.158
     1898787.251      400828.042
#Sta/Elev= 30
       0  962.59      10  960.28      20  956.65      30  951.12      50  937.23
      70  925.38      80   919.8      90  914.92     100  911.34     110  909.02
     120  907.53   180.1  900.19   220.1  896.15   260.1  893.42   270.1  891.18
   280.1  888.33   286.5   887.2   290.1  886.57   301.5  887.07   310.1  889.02
   320.1   891.9   330.1  893.29   400.2  891.08   410.2  891.34   420.2  892.82
   430.2  896.47   440.2  901.56   518.7  950.29     528  955.54   537.3  958.63
#Mann= 3 , 0 , 0
       0     .08       0   286.5    .045       0   301.5     .08       0
#XS Ineff= 2 , 0
                           338.4          893.33
Permanent Ineff=
       F       F
Bank Sta=286.5,301.5
XS Rating Curve= 0 ,0
Exp/Cntr=0.3,0.1

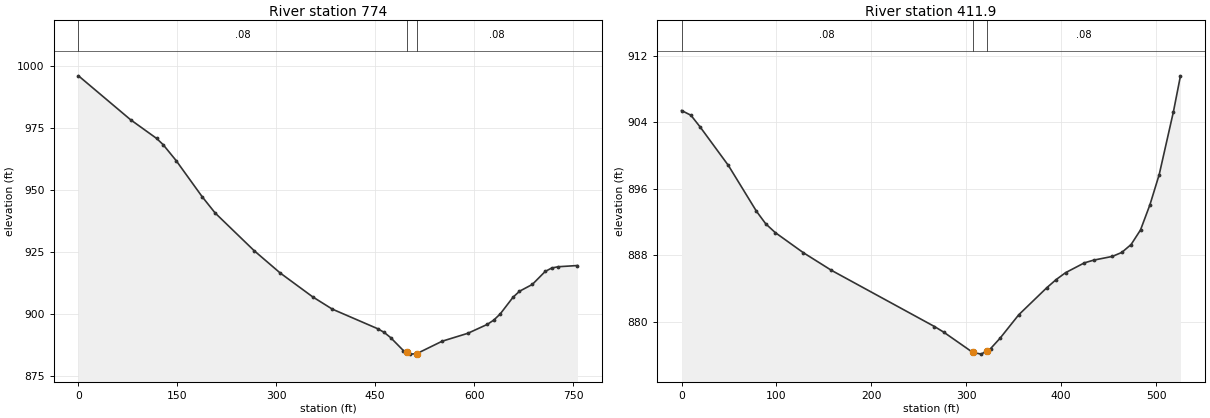
Type RM Length L Ch R = 1 ,774     ,389,362.1,335.1
XS GIS Cut Line= 3
     1898856.964      400048.039      1898767.52      400472.898
     1898701.753      400788.582
#Sta/Elev= 30
       0  996.17    78.9  978.46   118.4  970.91   128.3   968.4     148  961.98
   187.5  947.38   207.2   940.8   266.4  925.57   305.9  916.56   355.2  906.92
   384.8  901.99   453.7  894.07   463.5  892.59   473.3  890.49   492.8  885.21
   497.7  884.51   502.6  883.81   512.7  883.97   551.4  889.02   590.5  892.23
   619.8   895.8   629.6  897.52   639.4     900   658.9  906.76   668.7  909.19
   688.2  911.95   707.8  917.21   717.6  918.57   727.3  919.09   756.6  919.58
#Mann= 3 , 0 , 0
       0     .08       0   497.7    .045       0   512.7     .08       0
Bank Sta=497.7,512.7
XS Rating Curve= 0 ,0
Exp/Cntr=0.3,0.1

Type RM Length L Ch R = 1 ,411.9   ,426.1,411.9,397.7
XS GIS Cut Line= 3
      1898261.11       400446.59     1898688.599      400712.291
     1898705.699       400726.76
#Sta/Elev= 30
       0  905.43     9.9  904.86    19.7  903.44    49.4  898.82      79  893.31
    88.8   891.8    98.7  890.76   128.3  888.34   157.9  886.22   266.5  879.46
   276.3  878.78   306.8  876.35   315.8  876.14   321.8  876.55   325.7  876.81
   335.6  878.05   355.3  880.87   384.9  884.13   394.8  885.11   404.6  885.93
   424.4  887.11   434.2  887.44     454  887.89   463.9  888.37   473.7  889.32
   483.6  891.07   493.5  894.09   503.3  897.73   518.3   905.3   525.7   909.6
#Mann= 3 , 0 , 0
       0     .08       0   306.8    .045       0   321.8     .08       0
Bank Sta=306.8,321.8
XS Rating Curve= 0 ,0
Exp/Cntr=0.3,0.1

Chan Stop Cuts=-1
Use User Specified Reach Order=0
Composite Channel Slope=5